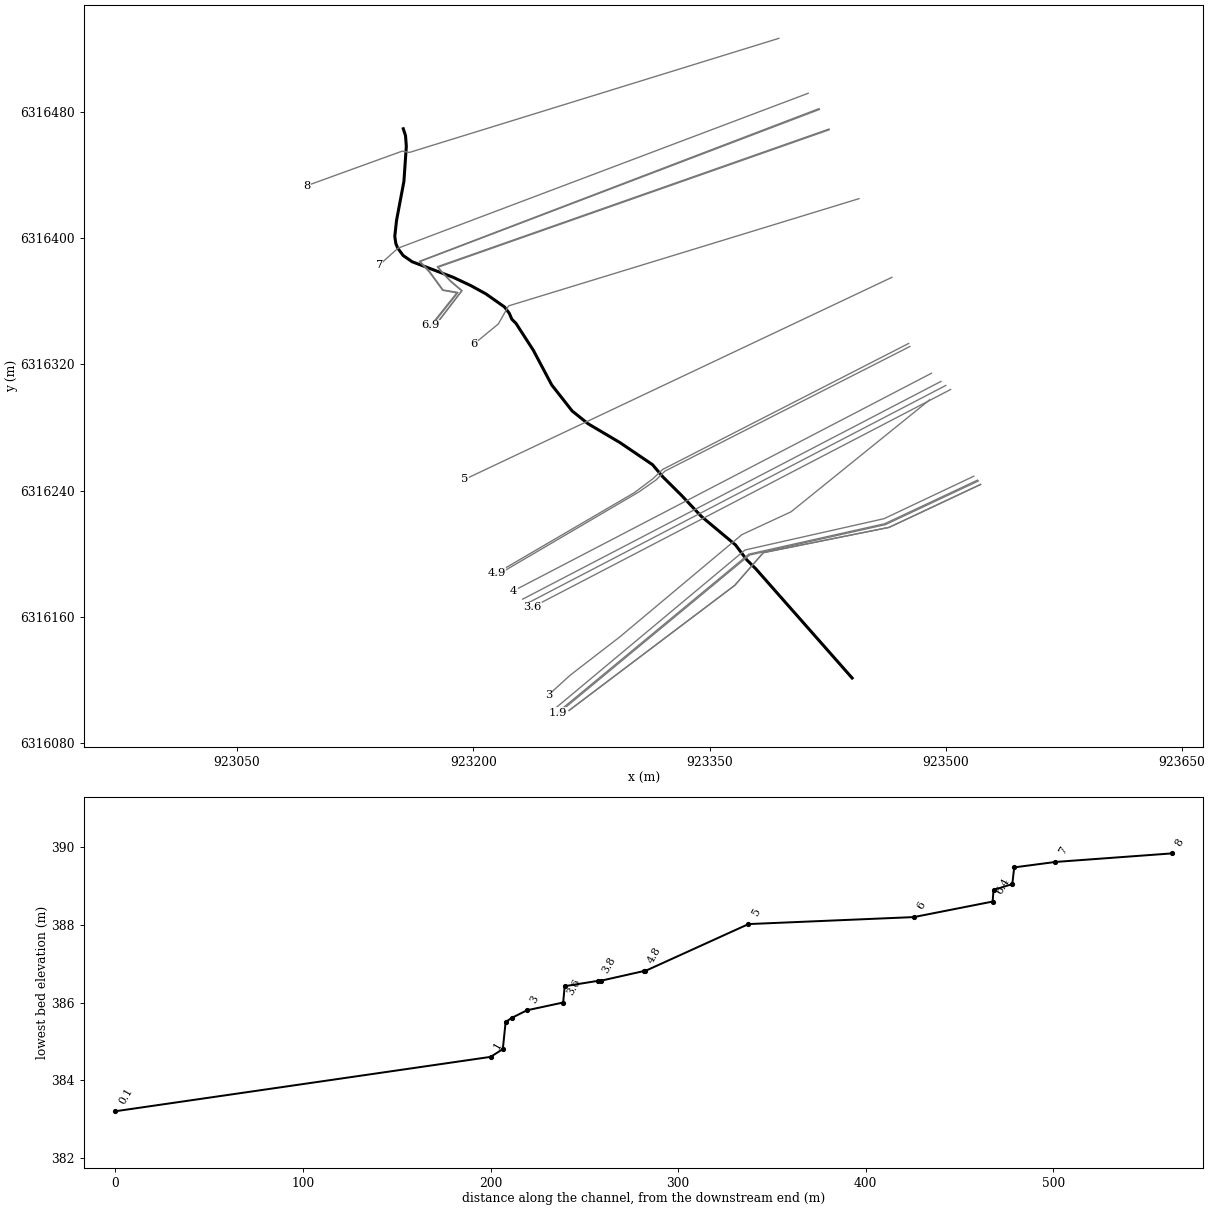
--- eau_vive.prj (project) ---

Proj Title=Eau_Vive_lit_min
Current Plan=p32
Default Exp/Contr=0.3,0.1
SI Units
Geom File=g03
Geom File=g01
Geom File=g02
Geom File=g04
Geom File=g05
Geom File=g06
Geom File=g07
Geom File=g08
Geom File=g09
Geom File=g10
Geom File=g11
Flow File=f02
Flow File=f01
Plan File=p06
Plan File=p01
Plan File=p02
Plan File=p03
Plan File=p04
Plan File=p05
Plan File=p07
Plan File=p08
Plan File=p09
Plan File=p10
Plan File=p11
Plan File=p12
Plan File=p13
Plan File=p14
Plan File=p15
Plan File=p16
Plan File=p17
Plan File=p18
Plan File=p19
Plan File=p20
Plan File=p21
Plan File=p22
Plan File=p23
Plan File=p24
Plan File=p25
Plan File=p26
Plan File=p27
Plan File=p28
Plan File=p29
Plan File=p30
Plan File=p31
Plan File=p32
Y Axis Title=Elevation
X Axis Title(PF)=Main Channel Distance
X Axis Title(XS)=Station
BEGIN DESCRIPTION:
END DESCRIPTION:
DSS Export Rating Curves= 0
DSS Export Rating Curve Sorted= 0
DSS Export Volume Flow Curves= 0
DXF OffsetX= 0
DXF OffsetY= 0
DXF ScaleX= 1
DXF ScaleY= 10

--- eau_vive.p32 (plan) ---

Plan Title=Plan 32
Program Version=4.10
Short Identifier=Plan 29
Geom File=g08
Flow File=f02
Mixed Flow
K Sum by GR= 0
Std Step Tol= 0.003
Critical Tol= 0.003
Num of Std Step Trials= 20
Max Error Tol= 0.1
Flow Tol Ratio= 0.001
Split Flow NTrial= 30
Split Flow Tol= 0.006
Split Flow Ratio= 0.02
Log Output Level= 0
Friction Slope Method= 1
Unsteady Friction Slope Method= 2
Unsteady Bridges Friction Slope Method= 1
Calc Critical at every XS
Parabolic Critical Depth
Global Vel Dist= 4 , 1 , 4
Global Log Level= 0
CheckData=True
Encroach Param=-1 ,0,0, 0
Computation Interval=1HOUR
Output Interval=1HOUR
Run HTab= 0
Run UNet= 0
Run PostProcess= 0
Run WQNet= 0
UNET Theta= 1
UNET Theta Warmup= 1
UNET ZTol= 0.006
UNET ZSATol= 0.015
UNET MxIter= 20
UNET MaxInSteps= 0
UNET DtIC= 0
UNET DtMin= 0
UNET MaxCRTS= 20
UNET WFStab= 2
UNET SFStab= 1
UNET WFX= 1
UNET SFX= 1
UNET DSS MLevel= 4
UNET DZMax Abort= 30
UNET Convert EG Bridges= 0
UNET Use Existing IB Tables=-1
UNET Froude Reduction=False
UNET Froude Limit= 1
UNET Froude Power= 10
UNET Time Slicing=0,0, 5
UNET Junction Losses=0
Instantaneous Interval=1HOUR
Write IC File= 0
Write IC File at Sim End=0
Echo Input=False
Echo Parameters=False
Echo Output=False
Write Detailed= 0
WQ AD Non Conservative
WQ ULTIMATE=-1
WQ Max Comp Step=1HOUR
WQ Output Interval=15MIN
WQ Output Selected Increments= 0
WQ Output face flow=0
WQ Output face velocity=0
WQ Output face area=0
WQ Output face dispersion=0
WQ Output cell volume=0
WQ Output cell surface area=0
WQ Output cell continuity=0
WQ Output cumulative cell continuity=0
WQ Output face conc=0
WQ Output face dconc_dx=0
WQ Output face courant=0
WQ Output face peclet=0
WQ Output face adv mass=0
WQ Output face disp mass=0
WQ Output cell mass=0
WQ Output cell source sink temp=0
WQ Output cell source sink nsm=0
WQ Output MaxMinRange=-1
WQ Daily Max Min Mean=-1
WQ Daily Range=0
WQ Daily Time=0
WQ Create Restart=0
WQ Fixed Restart=0
WQ System Summary=0
WQ Use Fixed Temperature=0
Sorting and Armoring Iterations= 10
XS Update Threshold= 0.02
Hydraulics Update Threshold= 0.02
Energy Slope Method= 1
Volume Change Method= 0
XS Weighting Method= 0
Number of US Weighted Cross Sections= 1
Number of DS Weighted Cross Sections= 1
Upstream XS Weight=0.25
Main XS Weight=0.5
Downstream XS Weight=0.25
Number of DS XS's Weighted with US Boundary= 1
Upstream Boundary Weight= 1
Weight of XSs Associated with US Boundary= 0
Number of US XS's Weighted with DS Boundary= 1
Downstream Boundary Weight= 0.5
Weight of XSs Associated with DS Boundary= 0.5
Sediment Output Level= 4
Mass or Volume Output= 0
Output Increment Type= 1
Profile and TS Output Increment= 10
XS Output Flag= 0
XS Output Increment= 10
Disregard all LS=0
Disregard all Conn=0
Disregard all Breaches=0
Disregard all Pumps=0

--- eau_vive.f02 (steady flow) ---

Flow Title=Eau_Vive_lit_min
Program Version=4.10
Number of Profiles= 2
Profile Names=PF 1,PF 2
River Rch & RM=Laye,Eau_Vive        ,8
      35     170
River Rch & RM=Laye,Eau_Vive        ,4.9
      35     170
Boundary for River Rch & Prof#=Laye,Eau_Vive        , 1
Up Type= 3
Up Slope=0.01
Dn Type= 3
Dn Slope=0.007
DSS Import GetInterval= 0
DSS Import GetPeak= 0
DSS Import FillOption= 0

--- eau_vive.g08 (geometry) ---

Geom Title=Eau_Vive_test
Program Version=4.10

River Reach=Laye            ,Eau_Vive
Reach XY= 30
923155.5737304696316469.33032227923156.9901123056316465.01672363
923157.5051269536316458.19207764923155.9730834966316435.97869873
923151.2894897466316411.25567627923150.1788940436316401.11547852
923150.8549194346316396.57647705923152.0139160166316393.72772217
 923155.49029541 6316388.9954834 923161.236511236316385.03588867
923187.2631225596316375.18548584923198.4656982426316369.92211914
923208.0748901376316364.65887451 923219.80871582 6316356.4019165
923222.8989257816316352.34570313923224.4924926766316348.62768555
923227.0999145516316346.02008057923238.1334838876316328.96691895
923249.7866821296316307.01251221923262.7921142586316290.46612549
923272.8356933596316282.41827393923293.1160888676316270.44329834
923313.8474731456316256.40771484923320.3499145516316248.74627686
923332.2990722666316236.89788818923344.865722656 6316223.6071167
923366.4932861336316205.58532715 923373.609497076316196.16027832
923379.3948974616316190.42907715923440.548052173 6316121.2121658

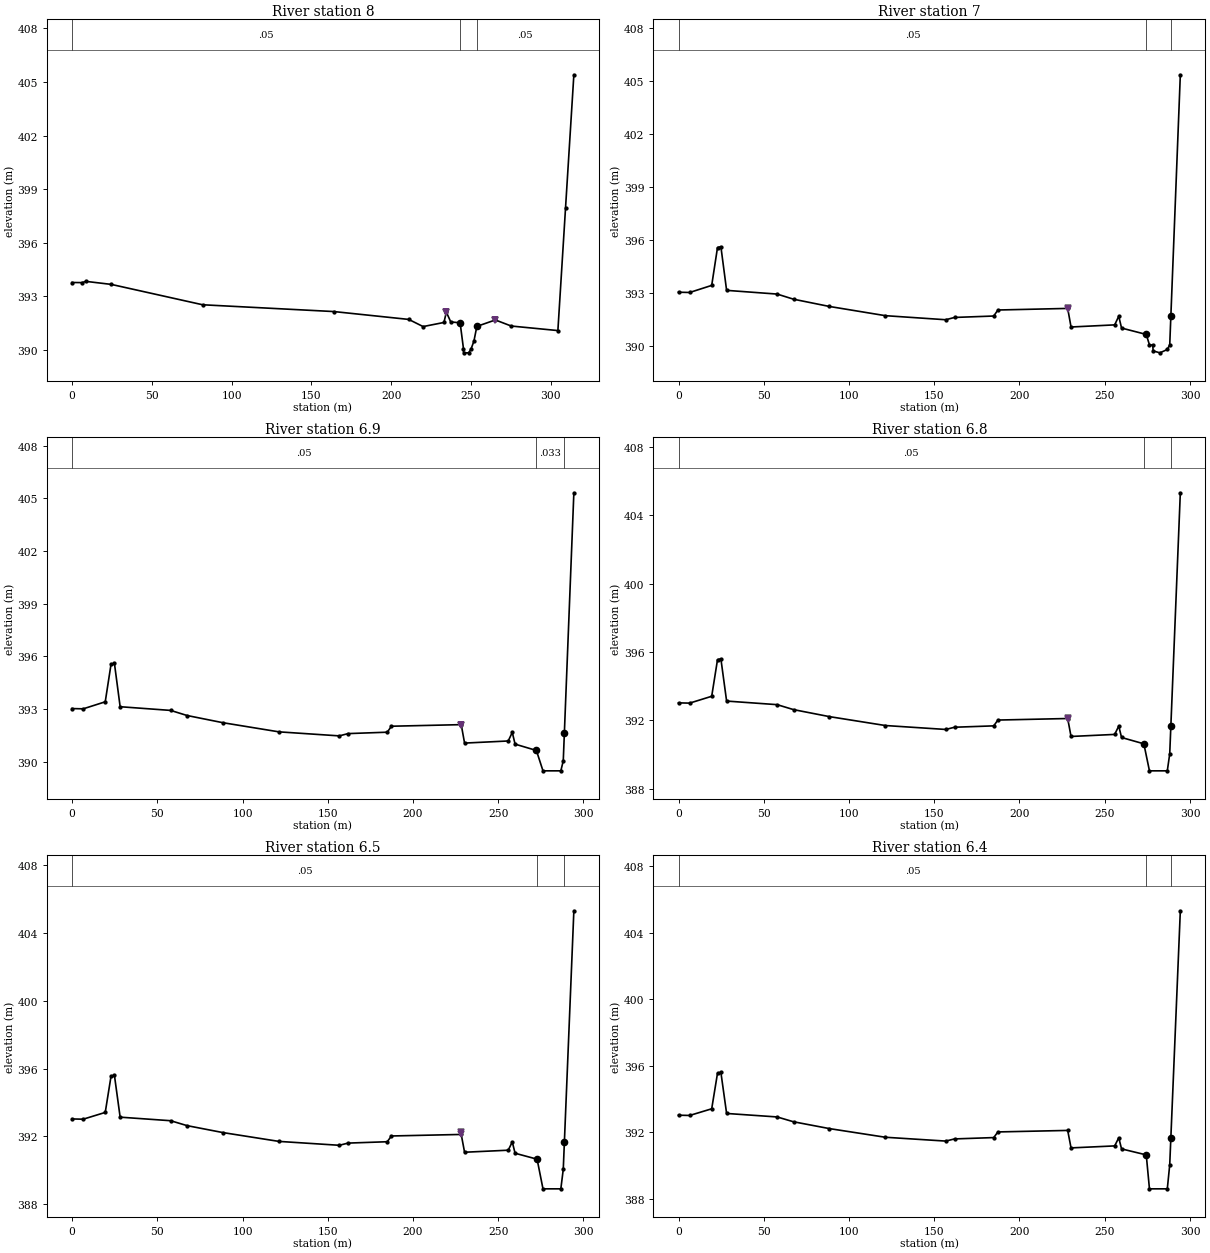
Type RM Length L Ch R = 1 ,8       ,60.91,62.03,63.22
Node Name=P1
XS GIS Cut Line= 6
 923394.045104986316526.65350342923159.457092285 6316454.3269043
923154.8840942386316455.16070557923150.1939086916316453.46429443
 923099.404479986316435.09307861923094.2493286136316433.24487305
#Sta/Elev= 23
       0 393.7766.411587  393.778.584955  393.8424.58639  393.6781.86146  392.53
 164.124  392.15211.0899  391.71220.0715  391.31233.1499  391.54  234.64  392.12
 237.409  391.57243.2848  391.52245.3734  390.08245.4844  389.84248.6192  389.84
250.1328 390.051 251.947   390.5253.7696  391.32265.3672  391.68275.3389  391.34
 304.574 391.086309.3499  397.92  314.59   405.4
#Mann= 3 , 0 , 0
       0     .05       0243.2848    .033       0253.7696     .05       0
Levee=-1,234.65,392.12,-1,265.37,391.68,,
Bank Sta=243.2848,253.7696
XS Rating Curve= 0 ,0
Exp/Cntr=0.3,0.1

Type RM Length L Ch R = 1 ,7       ,50,22,15
Node Name=P2
XS GIS Cut Line= 6
923412.6802978526316491.84051514 923402.654113776316488.06048584
 923158.91809082 6316396.1652832923152.2410888676316393.64807129
923144.439697266 6316386.6730957923140.3043212896316382.98187256
#Sta/Elev= 28
       0 393.0456.521074  393.0319.45695  393.43 22.8618  395.5724.84635  395.62
28.19994  393.1557.84393  392.9467.46356  392.65 88.5022  392.24121.3128  391.72
156.7458  391.49161.9153  391.62184.8927   391.7187.3443  392.04228.2868  392.13
230.2457  391.08255.8554   391.2258.2311  391.69259.8789  391.02274.3727  390.66
276.2444  390.07278.1817  390.06 278.392  389.73282.3771  389.62 286.717  389.81
288.1405  390.07288.7949  391.68294.3549  405.33
#Mann= 3 , 0 , 0
       0     .05       0274.3727    .033       0288.7949     .05       0
Levee=-1,228.34,392.16,0,,,,
Bank Sta=274.3727,288.7949
XS Rating Curve= 0 ,0
Exp/Cntr=0.3,0.1

Type RM Length L Ch R = 1 ,6.9     ,1,1,1
XS GIS Cut Line= 6
923419.469571574 6316482.0792569923165.7679520876316385.27906692
923171.9971980486316378.62093167923180.6291693646316366.91720736
923189.5458997296316365.33201085923173.0937288236316344.75748128
#Sta/Elev= 25
       0 393.0256.521074  393.0119.45695  393.41 22.8618  395.5524.84635   395.6
28.19994  393.1357.84393  392.9267.46356  392.63 88.5022  392.22121.3128   391.7
156.7458  391.47161.9153   391.6184.8927  391.68187.3443  392.02228.2868  392.11
230.2457  391.06255.8554  391.18258.2311  391.67259.8789     391272.3727  390.64
276.2444  389.48 286.717  389.48288.1405  390.05288.7949  391.66294.3549  405.31
#Mann= 3 , 0 , 0
       0     .05       0272.3727    .033       0288.7949     .05       0
Levee=-1,228.29,392.1,0,,,,
Bank Sta=272.3727,288.7949
XS Rating Curve= 0 ,0
Exp/Cntr=0.3,0.1

Type RM Length L Ch R = 1 ,6.8     ,12.6,10,7.9
XS GIS Cut Line= 6
923419.7275788186316481.56324241923166.2963509246316385.21301707
923172.1907034796316379.00794253923180.8273189276316367.18140677
923190.3384979846316365.59621026923173.6742451156316344.69297947
#Sta/Elev= 25
       0 393.0256.521074  393.0119.45695  393.41 22.8618  395.5524.84635   395.6
28.19994  393.1357.84393  392.9267.46356  392.63 88.5022  392.22121.3128   391.7
156.7458  391.47161.9153   391.6184.8927  391.68187.3443  392.02228.2868  392.11
230.2457  391.06255.8554  391.18258.2311  391.67259.8789     391  272.96  390.63
276.2444  389.05 286.717  389.05288.1405  390.05288.7949  391.66294.3549  405.31
#Mann= 3 , 0 , 0
       0     .05       0  272.96    .033       0288.7949     .05       0
Levee=-1,228.34,392.12,0,,,,
Bank Sta=272.96,288.7949
XS Rating Curve= 0 ,0
Exp/Cntr=0.3,0.1

Type RM Length L Ch R = 1 ,6.5     ,0.5,0.5,0.5
XS GIS Cut Line= 6
923425.9197526836316469.17889468923177.1268482016316381.87029019
923180.6784559296316377.68031925923185.8005854436316372.36425607
 923192.637777336316366.62359496923176.6847546116316345.59342462
#Sta/Elev= 25
       0 393.0256.521074  393.0119.45695  393.41 22.8618  395.5524.84635   395.6
28.19994  393.1357.84393  392.9267.46356  392.63 88.5022  392.22121.3128   391.7
156.7458  391.47161.9153   391.6184.8927  391.68187.3443  392.02228.2868  392.11
230.2457  391.06255.8554  391.18258.2311  391.67259.8789     391  272.79  390.65
276.2444   388.9 286.717   388.9288.1405  390.05288.7949  391.66294.3549  405.31
#Mann= 3 , 0 , 0
       0     .05       0  272.79    .033       0288.7949     .05       0
Levee=-1,228.04,392.25,0,,,,
Bank Sta=272.79,288.7949
XS Rating Curve= 0 ,0
Exp/Cntr=0.3,0.1

Type RM Length L Ch R = 1 ,6.4     ,51.2,42,40
XS GIS Cut Line= 6
923425.9197526836316468.66288019923177.6733573516316381.58801494
923181.1937669466316377.48507548923185.7360836326316372.81576874
923192.8957845716316366.68809677923176.4267473676316345.59342462
#Sta/Elev= 25
       0 393.0256.521074  393.0119.45695  393.41 22.8618  395.5524.84635   395.6
28.19994  393.1357.84393  392.9267.46356  392.63 88.5022  392.22121.3128   391.7
156.7458  391.47161.9153   391.6184.8927  391.68187.3443  392.02228.2868  392.11
230.2457  391.06255.8554  391.18258.2311  391.67259.8789     391274.3727  390.64
276.2444   388.6 286.717   388.6288.1405  390.05288.7949  391.66294.3549  405.31
#Mann= 3 , 0 , 0
       0     .05       0274.3727    .033       0288.7949     .05       0
Bank Sta=274.3727,288.7949
XS Rating Curve= 0 ,0
Exp/Cntr=0.3,0.1

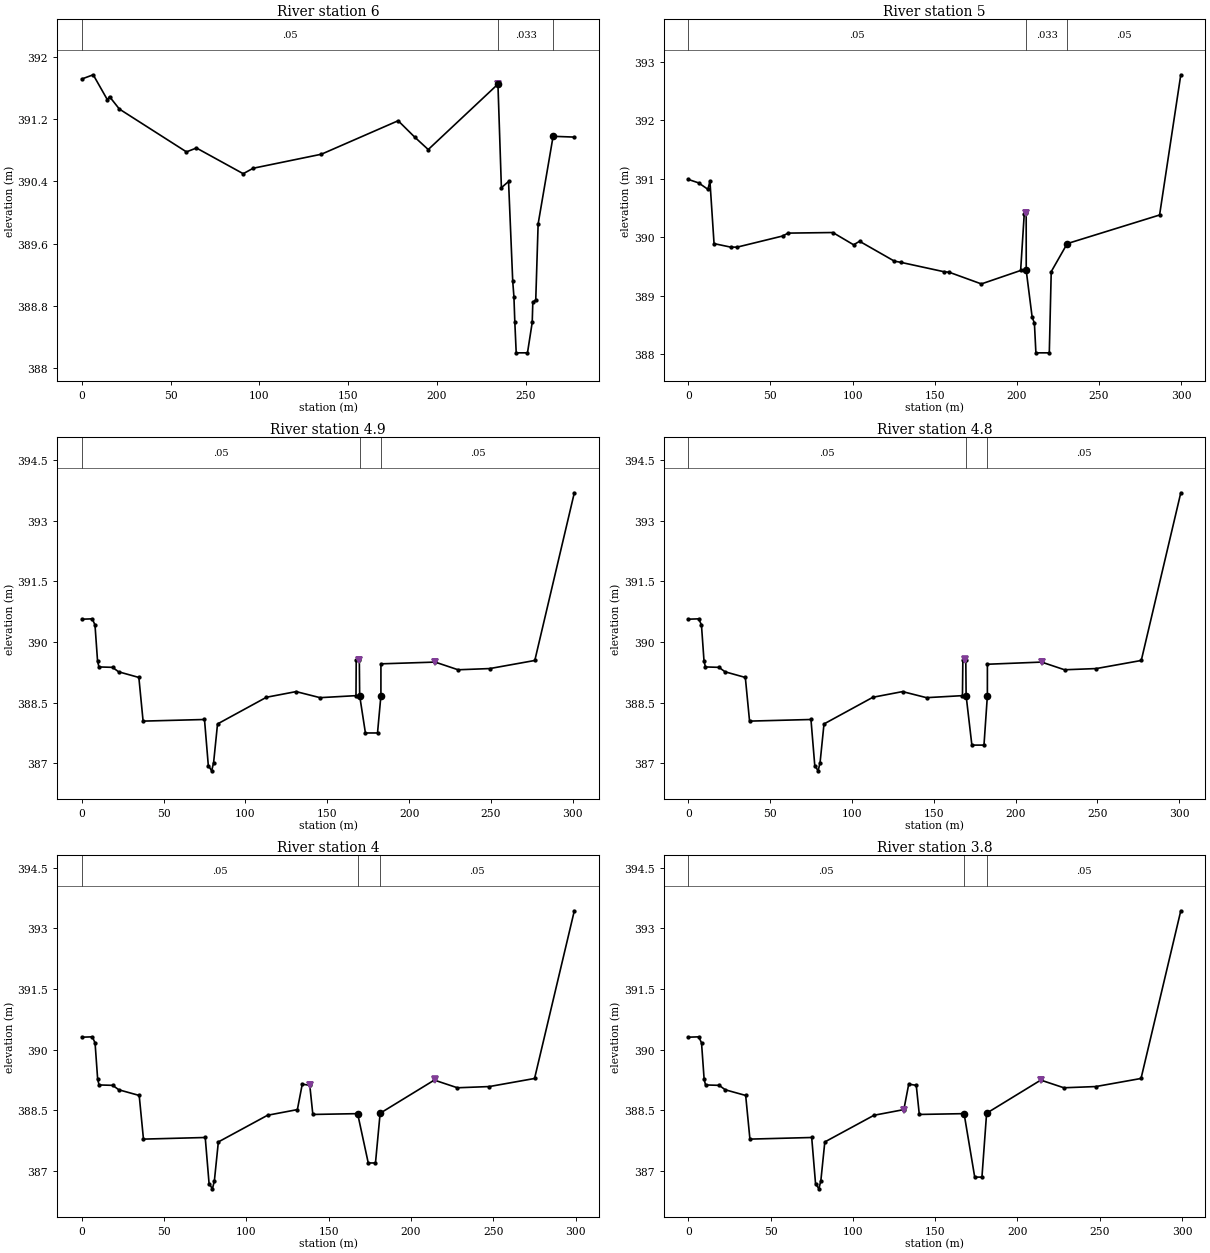
Type RM Length L Ch R = 1 ,6       ,89.5,88.15,86.54
Node Name=P3
XS GIS Cut Line= 6
923444.910522461 6316425.0335083 923435.015502936316422.01049805
923222.4224853526316357.06671143923221.5574951176316355.53991699
923215.9498901376316345.64367676923200.1896972666316332.71289063
#Sta/Elev= 27
       0 391.7166.396159  391.7714.36259  391.4515.57349  391.4921.13077  391.33
58.92574  390.7864.54691  390.8390.88918   390.596.50021  390.57134.9183  390.75
178.1652  391.18187.4754  390.97195.1084  390.81234.3692  391.65236.3141  390.32
 240.346   390.4242.6966  389.12243.3751  388.92243.8803 388.595244.6586   388.2
251.0086   388.2253.6763  388.59254.0157  388.85255.6695  388.88257.0093 389.855
265.4427  390.98277.3955  390.97
#Mann= 3 , 0 , 0
       0     .05       0234.3692    .033       0265.4427     .05       0
Levee=-1,234.36,391.65,0,,,,
Bank Sta=234.3692,265.4427
XS Rating Curve= 0 ,0
Exp/Cntr=0.3,0.1

Type RM Length L Ch R = 1 ,5       ,55,55,55
Node Name=P4
XS GIS Cut Line= 3
 923465.810485846316375.17449951923264.2192993166316279.99127197
923194.6862792976316247.16052246
#Sta/Elev= 29
       0 390.989 6.26795  390.9311.92126  390.8213.15991  390.9615.66226  389.89
25.82419  389.8329.72534  389.8357.35895  390.0260.76714  390.0787.98922  390.08
100.6271  389.87104.2697  389.93125.4556  389.59129.3218  389.57155.4645  389.41
158.8199   389.4178.4155   389.2 202.322  389.43   204.5  390.39   205.7  390.42
205.7239  389.43209.3334  388.63210.7027  388.53211.6116  388.02219.7704  388.02
220.9447  389.41230.6678  389.89 286.912  390.38299.8263 392.781
#Mann= 3 , 0 , 0
       0     .05       0205.7239    .033       0230.6678     .05       0
Levee=-1,205.67,390.42,0,,,,
Bank Sta=205.7239,230.6678
XS Rating Curve= 0 ,0
Exp/Cntr=0.3,0.1

Type RM Length L Ch R = 1 ,4.9     ,0.5,0.5,0.5
XS GIS Cut Line= 5
923476.4467400276316333.26645552923320.2207638356316253.38364482
923314.2260089756316247.63864816923302.1650600466316238.61079627
923214.8958250666316187.72654013
#Sta/Elev= 30
       0390.56436.344949390.57338.026225390.42329.608204389.5233 10.4616389.3833
18.75083389.373322.45152389.263334.84264389.123337.43143388.043374.96304388.0833
77.29465386.943379.33465386.813380.52125387.013382.93068387.9733112.8225388.6333
130.9512388.7733145.5885388.6233167.5552388.6732   167.7  389.55   169.6  389.55
   169.8388.6732173.3152  387.75180.7152  387.75  182.79388.6732   182.8  389.46
215.9356389.5033229.9619389.3133249.3694389.3433276.8486389.5433301.0074393.6913
#Mann= 3 , 0 , 0
       0     .05       0   169.8    .033       0  182.79     .05       0
Levee=-1,169.58,389.56,-1,215.92,389.51,,
Bank Sta=169.8,182.79
XS Rating Curve= 0 ,0
Exp/Cntr=0.3,0.1

Type RM Length L Ch R = 1 ,4.8     ,23,23.3,23.7
XS GIS Cut Line= 5
923477.2674538366316331.35145664923321.6124332526316252.28935974
923316.1410078626316246.81793435923305.1743440116316239.15793881
923215.4429676056316186.63225506
#Sta/Elev= 30
       0390.56436.344949390.57338.026225390.42329.608204389.5233 10.4616389.3833
18.75083389.373322.45152389.263334.84264389.123337.43143388.043374.96304388.0833
77.29465386.943379.33465386.813380.52125387.013382.93068387.9733112.8225388.6333
130.9512388.7733145.5885388.6233167.5552388.6732   167.8  389.55   169.6  389.55
   169.8  388.67173.3152  387.45180.7152  387.45  182.79388.6732   182.8  389.45
215.9356389.5033229.9619389.3133249.3694389.3433276.8486389.5433301.0074393.6913
#Mann= 3 , 0 , 0
       0     .05       0   169.8    .033       0  182.79     .05       0
Levee=-1,169.38,389.57,-1,215.92,389.5,,
Bank Sta=169.8,182.79
XS Rating Curve= 0 ,0
Exp/Cntr=0.3,0.1

Type RM Length L Ch R = 1 ,4       ,1.2,1.2,1.2
Node Name=P5
XS GIS Cut Line= 3
923490.9550781256316314.39550781923288.525085449 6316209.1953125
923225.4522705086316176.41711426
#Sta/Elev= 28
       0 390.3116.344949  390.328.026225  390.179.608204  389.27 10.4616  389.13
18.75083  389.1222.45152  389.0134.84264  388.8737.43143  387.7974.96304  387.83
77.29465  386.6979.33465  386.5680.52125  386.7682.93068  387.72112.8225  388.38
130.9512  388.52 133.917  389.15138.4908  389.12140.3434   388.4167.5552  388.42
174.0115   387.2178.3992   387.2181.2331  388.43214.1435  389.25228.1698  389.06
247.5773  389.09275.0565  389.29299.2153 393.438
#Mann= 3 , 0 , 0
       0     .05       0167.5552    .033       0181.2331     .05       0
Levee=-1,138.42,389.12,-1,214.31,389.27,,
Bank Sta=167.5552,181.2331
XS Rating Curve= 0 ,0
Exp/Cntr=0.3,0.1

Type RM Length L Ch R = 1 ,3.8     ,18,18,18
XS GIS Cut Line= 3
923496.9445742676316309.19694883923294.5145815916316203.99675352
 923231.441766656316171.21855528
#Sta/Elev= 28
       0 390.3116.344949  390.328.026225  390.179.608204  389.27 10.4616  389.13
18.75083  389.1222.45152  389.0134.84264  388.8737.43143  387.7974.96304  387.83
77.29465  386.6979.33465  386.5680.52125  386.7682.93068  387.72112.8225  388.38
130.9512  388.52 133.917  389.15138.4908  389.12140.3434   388.4167.5552  388.42
174.0115  386.85178.3992  386.85181.2331  388.43214.1435  389.25228.1698  389.06
247.5773  389.09275.0565  389.29299.2153 393.438
#Mann= 3 , 0 , 0
       0     .05       0167.5552    .033       0181.2331     .05       0
Levee=-1,130.82,388.52,-1,214.14,389.25,,
Bank Sta=167.5552,181.2331
XS Rating Curve= 0 ,0
Exp/Cntr=0.3,0.1

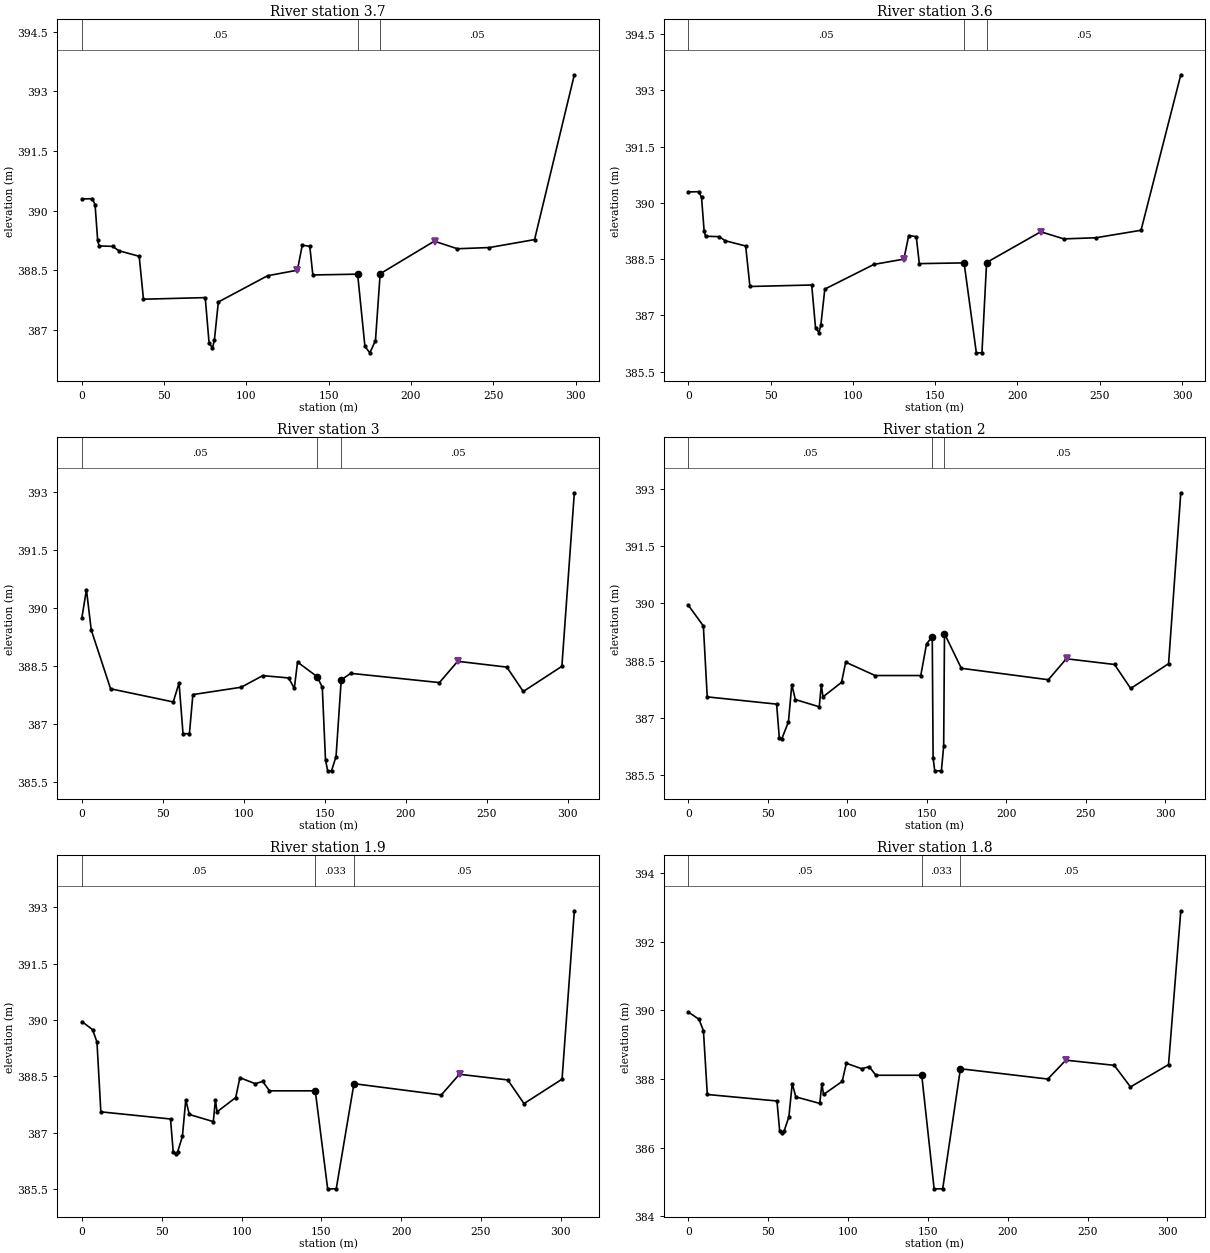
Type RM Length L Ch R = 1 ,3.7     ,0.8,0.8,0.8
XS GIS Cut Line= 3
923499.9898252646316306.62391504923297.5598325886316201.42371973
923234.4870176476316168.64552149
#Sta/Elev= 29
       0 390.2916.344949   390.38.026225  390.159.608204  389.25 10.4616  389.11
18.75083   389.122.45152  388.9934.84264  388.8537.43143  387.7774.96304  387.81
77.29465  386.6779.33465  386.5480.52125  386.7482.93068   387.7112.8225  388.36
130.9512   388.5 133.917  389.13138.4908   389.1140.3434  388.38167.5552   388.4
     172  386.58     175  386.42178.3992  386.73181.2331  388.41214.1435  389.23
228.1698  389.04247.5773  389.07275.0565  389.27299.2153 393.418
#Mann= 3 , 0 , 0
       0     .05       0167.5552    .033       0181.2331     .05       0
Levee=-1,130.99,388.5,-1,214.31,389.22,,
Bank Sta=167.5552,181.2331
XS Rating Curve= 0 ,0
Exp/Cntr=0.3,0.1

Type RM Length L Ch R = 1 ,3.6     ,19,19.3,19.07
XS GIS Cut Line= 3
923503.0711412166316304.06962373 923300.641148546316198.86942842
923237.5683335996316166.09123018
#Sta/Elev= 28
       0 390.2916.344949   390.38.026225  390.159.608204  389.25 10.4616  389.11
18.75083   389.122.45152  388.9934.84264  388.8537.43143  387.7774.96304  387.81
77.29465  386.6779.33465  386.5480.52125  386.7482.93068   387.7112.8225  388.36
130.9512   388.5 133.917  389.13138.4908   389.1140.3434  388.38167.5552   388.4
     175     386178.3992     386181.2331  388.41214.1435  389.23228.1698  389.04
247.5773  389.07275.0565  389.27299.2153 393.418
#Mann= 3 , 0 , 0
       0     .05       0167.5552    .033       0181.2331     .05       0
Levee=-1,130.82,388.5,-1,214.14,389.23,,
Bank Sta=167.5552,181.2331
XS Rating Curve= 0 ,0
Exp/Cntr=0.3,0.1

Type RM Length L Ch R = 1 ,3       ,7.78,7.88,7.97
Node Name=P7
XS GIS Cut Line= 6
923489.8521695356316297.58218587923401.7965549286316226.56959344
 923370.575555296316212.10163408923293.0827316166316147.29371754
923261.5789633416316123.02032231923247.6346724656316110.36716948
#Sta/Elev= 28
       0  389.75    2.83  390.48    5.79  389.44   17.73  387.92   56.42  387.58
      60  388.07   62.46  386.76   66.41  386.76   68.54  387.77   98.37  387.96
  111.66  388.26  127.65   388.2  131.15  387.93  133.15  388.61  145.32  388.23
148.4187  387.96150.4115  386.08151.7674   385.8154.1194   385.8156.9235  386.17
160.1076  388.15165.9992 388.319220.7225  388.08232.0206  388.63262.3434  388.48
272.5041  387.85296.3322   388.5304.0156 392.984
#Mann= 3 , 0 , 0
       0     .05       0  145.32    .033       0160.1076     .05       0
Levee=0,,,-1,232.28,388.65,,
Bank Sta=145.32,160.1076
XS Rating Curve= 0 ,0
Exp/Cntr=0.3,0.1

Type RM Length L Ch R = 1 ,2       ,3.5,3.5,3.5
Node Name=P6
XS GIS Cut Line= 6
923517.7614746096316249.09448242923490.4810791026316236.21032715
 923460.822082526316222.20288086923372.5930786136316202.36767578
923307.1262817386316147.83752441923252.4984741216316102.33551025
#Sta/Elev= 30
       0 389.9549.460953  389.4111.89843  387.5555.52702  387.3657.21478  386.48
58.69991  386.4462.96964 386.89665.07301  387.8767.30621  387.4882.32803  387.29
83.64318  387.8784.66817  387.5596.35469  387.93 98.9673  388.46117.4914  388.11
 146.184  388.11149.8063  388.94153.4007 389.129153.9411  385.94154.9656  385.61
159.1406  385.61160.5905  386.26161.0968  389.21171.6827   388.3226.4061     388
237.7042  388.55 268.027   388.4278.1877  387.77302.0158  388.42309.6992 392.904
#Mann= 3 , 0 , 0
       0     .05       0153.4007    .033       0161.0968     .05       0
Levee=0,,,-1,238,388.56,,
Bank Sta=153.4007,161.0968
XS Rating Curve= 0 ,0
Exp/Cntr=0.3,0.1

Type RM Length L Ch R = 1 ,1.9     ,1.5,1.5,1.5
XS GIS Cut Line= 6
923520.1603528986316246.62346398923461.2567805756316218.99347378
923374.9911132096316199.70321265923372.4682909466316197.63552269
923369.9454686836316195.56783274923253.4531414376316099.33011906
#Sta/Elev= 29
       0 389.9546.691993  389.749.460953  389.4111.89843  387.5555.52702  387.36
57.21478  386.4858.69991  386.4460.02131  386.4962.96964 386.89665.07301  387.87
67.30621  387.4882.32803  387.2983.64318  387.8784.66817  387.5596.35469  387.93
 98.9673  388.46108.5669   388.3113.2747  388.36117.4914  388.11 146.184  388.11
153.9411   385.5159.3111   385.5170.4033   388.3225.1266     388236.4247  388.55
266.7476   388.4276.9082  387.77300.7364  388.42308.4197 392.904
#Mann= 3 , 0 , 0
       0     .05       0 146.184    .033       0170.4033     .05       0
Levee=0,,,-1,236.62,388.55,,
Bank Sta=146.184,170.4033
XS Rating Curve= 0 ,0
Exp/Cntr=0.3,0.1

Type RM Length L Ch R = 1 ,1.8     ,6.5,6.5,6.5
XS GIS Cut Line= 6
923520.6615876996316246.08862162923461.7580153766316218.45863142
923383.0110394226316200.84965932 923375.492348016316199.16837029
923370.4467034846316195.03299038923253.954376238 6316098.7952767
#Sta/Elev= 29
       0 389.9546.691993  389.749.460953  389.4111.89843  387.5555.52702  387.36
57.21478  386.4858.69991  386.4460.02131  386.4962.96964 386.89665.07301  387.87
67.30621  387.4882.32803  387.2983.64318  387.8784.66817  387.5596.35469  387.93
 98.9673  388.46108.5669   388.3113.2747  388.36117.4914  388.11 146.184  388.11
153.9411   384.8159.3111   384.8170.4033   388.3225.1266     388236.4247  388.55
266.7476   388.4276.9082  387.77300.7364  388.42308.4197 392.904
#Mann= 3 , 0 , 0
       0     .05       0 146.184    .033       0170.4033     .05       0
Levee=0,,,-1,236.62,388.56,,
Bank Sta=146.184,170.4033
XS Rating Curve= 0 ,0
Exp/Cntr=0.3,0.1

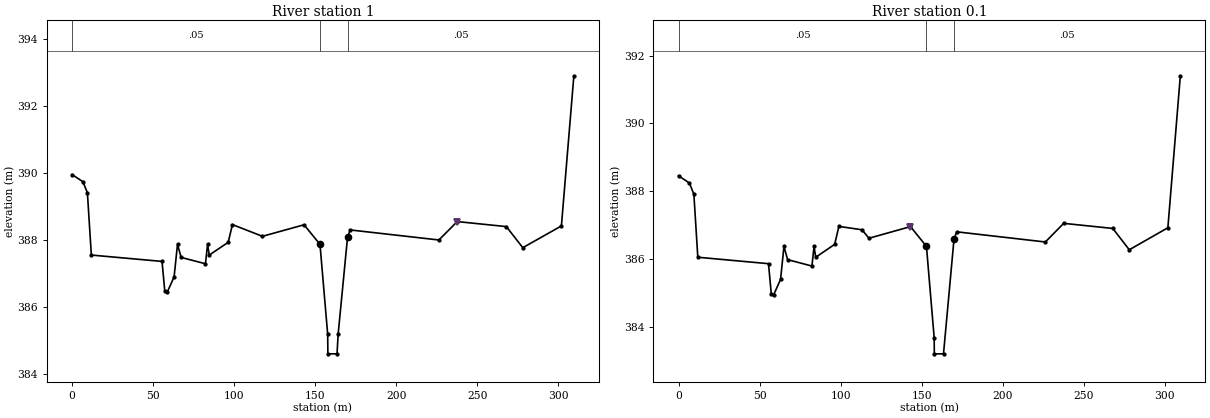
Type RM Length L Ch R = 1 ,1       ,200,200,200
Node Name=P8
XS GIS Cut Line= 5
923522.1167056426316243.89672589923464.0902245166316216.70717474
923384.1573514166316200.64717357923366.0371657756316179.95226986
923260.8317506266316100.65421249
#Sta/Elev= 30
       0 389.9546.691993  389.749.460953  389.4111.89843  387.5555.52702  387.36
57.21478  386.4858.69991  386.4462.96964 386.89665.07301  387.8767.30621  387.48
82.32803  387.2983.64318  387.8784.66817  387.5596.35469  387.93 98.9673  388.46
117.4914  388.11143.1653 388.454153.0141  387.87157.7675  385.18157.8801   384.6
163.5354   384.6164.2043  385.18     170 388.076171.6827   388.3226.4061     388
237.7042  388.55 268.027   388.4278.1877  387.77302.0158  388.42309.6992 392.904
#Mann= 3 , 0 , 0
       0     .05       0153.0141    .033       0     170     .05       0
Levee=0,,,-1,237.61,388.55,,
Bank Sta=153.0141,170
XS Rating Curve= 0 ,0
Exp/Cntr=0.3,0.1

Type RM Length L Ch R = 1 ,0.1     ,0,0,0
XS GIS Cut Line= 5
923522.1167056426316243.89672589923464.0902245166316216.70717474
923384.1573514166316200.64717357923366.0371657756316179.95226986
923260.8317506266316100.65421249
#Sta/Elev= 30
       0 388.4546.691993  388.249.460953  387.9111.89843  386.0555.52702  385.86
57.21478  384.9858.69991  384.9462.96964 385.39665.07301  386.3767.30621  385.98
82.32803  385.7983.64318  386.3784.66817  386.0596.35469  386.43 98.9673  386.96
113.2747  386.86117.4914  386.61143.1653 386.954153.0141  386.37157.7675  383.68
157.8801   383.2163.5354   383.2     170 386.576171.6827   386.8226.4061   386.5
237.7042  387.05 268.027   386.9278.1877  386.27302.0158  386.92309.6992 391.404
#Mann= 3 , 0 , 0
       0     .05       0153.0141    .033       0     170     .05       0
Levee=-1,143.15,386.94,0,,,,
Bank Sta=153.0141,170
XS Rating Curve= 0 ,0
Exp/Cntr=0.3,0.1

Chan Stop Cuts=-1
Use User Specified Reach Order=0
Composite Channel Slope=5